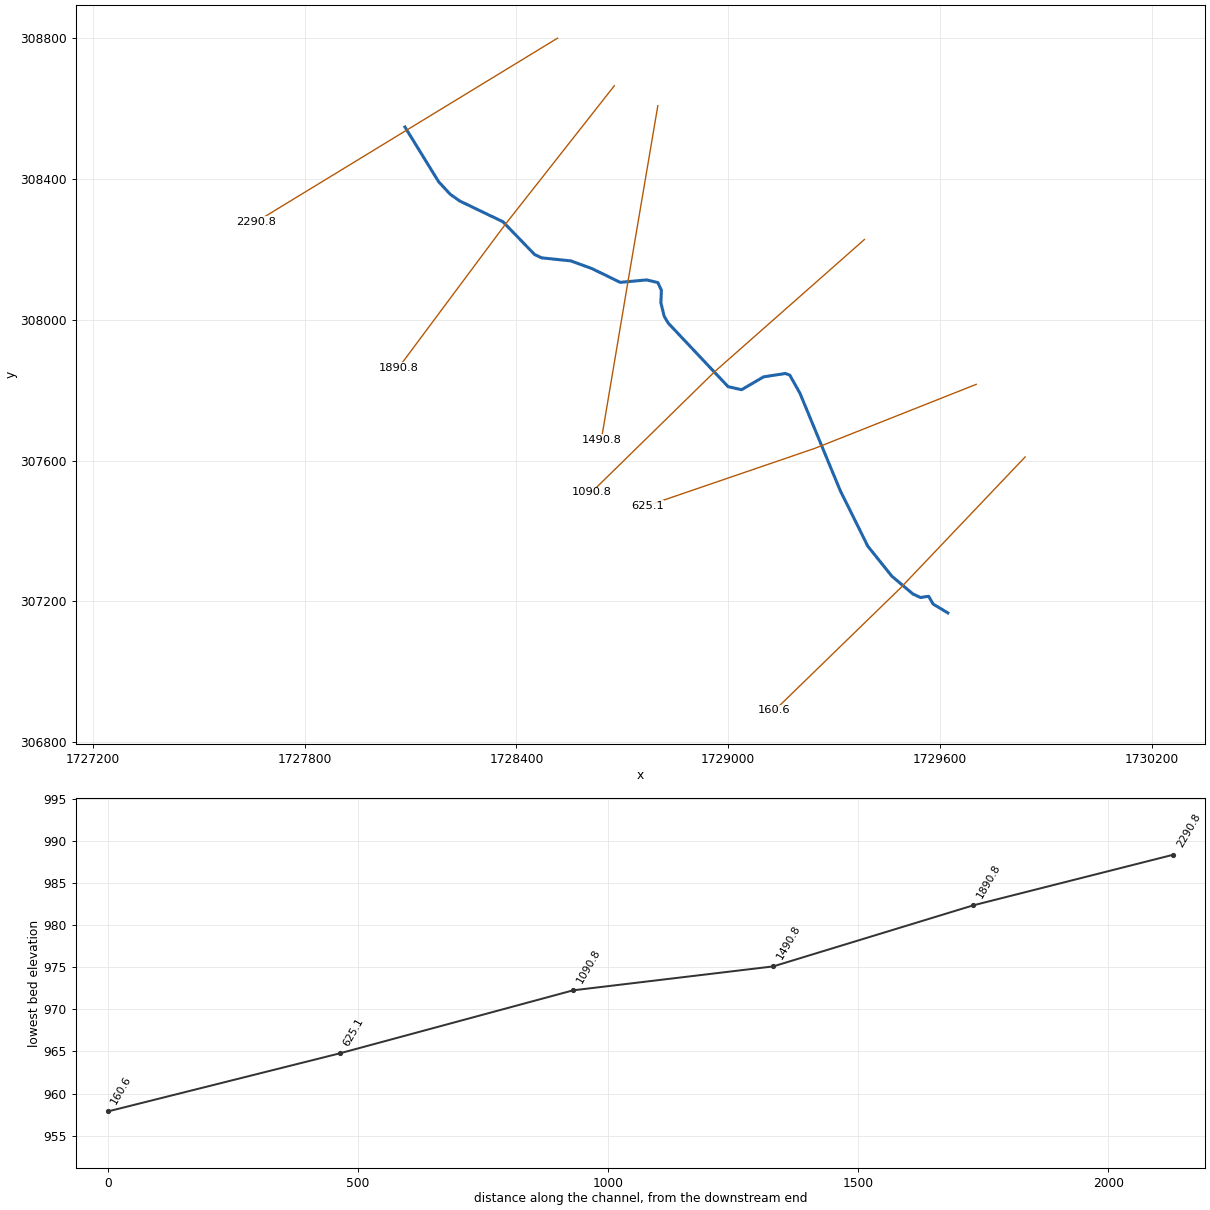
--- LmbrtRnT1.prj (project) ---

Proj Title=LmbrtRnT1
Current Plan=p01
Geom File=g01
Flow File=f01
Plan File=p01
DSS Export Rating Curves=0
DSS Export Rating Curve Sorted=0
DSS Export Volume Flow Curves=0
DXF OffsetX=0
DXF OffsetY=0
DXF ScaleX=0
DXF ScaleY=0

--- LmbrtRnT1.p01 (plan) ---

Plan Title=Floodplain
Program Version=4.00
Geom File=g01
Flow File=f01
K Sum by GR=0
Std Step Tol=0.01
Critical Tol=0.01
Num of Std Step Trials=20
Max Error Tol=0.3
Flow Tol Ratio=0.001
Split Flow NTrial=30
Split Flow Tol=0.02
Split Flow Ratio=0.02
Log Output Level=0
Friction Slope Method=1
Unsteady Friction Slope Method=2
Unsteady Bridges Friction Slope Method=1
Global Log Level=0
CheckData=False
Run HTab=0
Run UNet=0
Run PostProcess=0
UNET Theta=0
UNET Theta Warmup=0
UNET ZTol=0
UNET ZSATol=0
UNET MxIter=0
UNET MaxInSteps=0
UNET DtIC=0
UNET DtMin=0
UNET MaxCRTS=0
UNET WFStab=0
UNET SFStab=0
UNET WFX=0
UNET SFX=0
UNET DSS MLevel=0
UNET DZMax Abort=0
UNET Convert EG Bridges=0
UNET Use Existing IB Tables=0
UNET Froude Limit=0
UNET Froude Power=0
Write IC File=0
Echo Input=False
Echo Output=False
Write Detailed=0

--- LmbrtRnT1.f01 (steady flow) ---

Flow Title=NFF Regression Equation
Program Version=4.00
Number of Profiles=1
Profile Names=P100yr
River Rch & RM=LmbrtRnT1,Main      ,2290.8
808.5590
River Rch & RM=LmbrtRnT1,Main      ,160.6
847.6105
Boundary for River Rch & Prof#=LmbrtRnT1,Main      ,1
Up Type=0
Dn Type=3
Dn Slope=0.013687

--- LmbrtRnT1.g01 (geometry) ---

Geom Title=USGS 3m DEM
Program Version=4.00

River Reach=LmbrtRnT1     ,Main
Reach XY= 30
     1728083.984      308547.382     1728179.535      308391.852
     1728212.421      308356.423     1728239.051      308337.477
     1728361.648      308278.407     1728451.550      308185.333
     1728471.650      308175.900     1728553.998      308167.275
     1728614.363      308145.300     1728693.796      308106.306
     1728769.062      308113.260     1728800.911      308105.567
     1728810.831      308083.827     1728809.336      308048.318
     1728818.688      308010.098     1728830.177      307990.574
     1728999.884      307810.093     1729038.050      307801.421
     1729100.681      307838.009     1729162.243      307847.511
     1729174.783      307842.821     1729203.560      307791.331
     1729316.763      307517.153     1729395.828      307357.028
     1729464.173      307271.694     1729523.931      307221.096
     1729545.272      307211.289     1729568.313      307214.774
     1729580.865      307192.869     1729622.738      307167.496

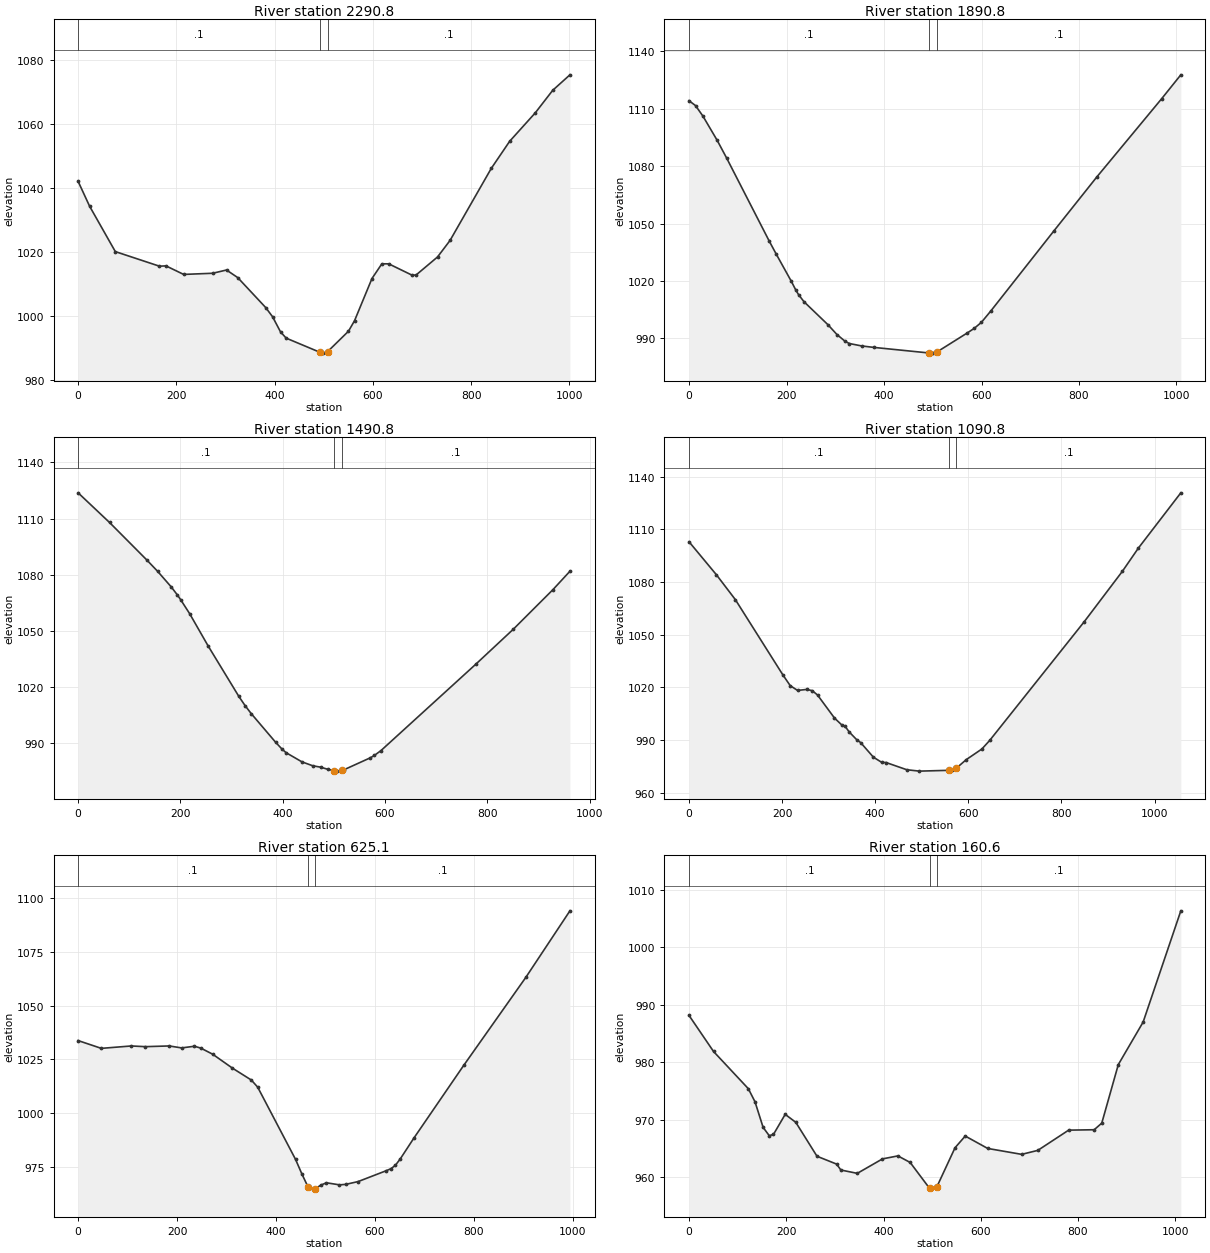
Type RM Length L Ch R = 1 ,2290.8,391.951,400,408.653
XS GIS Cut Line= 3
     1728516.332      308799.722     1728089.197      308538.847
     1727662.061      308277.972
#Sta/Elev= 30
       0 1042.11    23.3 1034.35    75.7 1020.13   165.4 1015.57   178.8 1015.66
   214.8 1012.99   273.8 1013.35   302.0 1014.37   324.8 1012.00   381.7 1002.63
   395.7  999.75   412.0  994.99   423.5  993.04   493.0  988.56   498.3  988.35
     508  988.85   550.2  995.20   562.6  998.50   598.1 1011.71   618.2 1016.31
   632.2 1016.30   679.7 1012.75   687.8 1012.80   731.5 1018.45   757.0 1023.63
   840.8 1046.16   878.4 1054.68   930.2 1063.52   966.0 1070.63  1001.0 1075.47
#Mann= 3 , 0 , 0
       0     0.1       0     493   0.045       0     508     0.1       0
Bank Sta=     493,     508
Exp/Cntr=0.3,0.1

Type RM Length L Ch R = 1 ,1890.8,388.917,400,410.512
XS GIS Cut Line= 3
     1728677.371      308664.604     1728368.501      308271.127
     1728064.950      307862.899
#Sta/Elev= 30
       0 1114.12    13.3 1111.57    28.4 1106.12    57.8 1093.41    77.0 1084.26
   164.2 1040.99   179.3 1033.84   209.5 1020.00   218.9 1015.35   224.6 1012.91
   235.8 1009.19   285.0  997.17   303.4  992.06   320.3  988.49   328.8  987.36
   354.2  986.09   379.5  985.32   492.7  982.41   496.3  982.34   500.0  982.39
   507.7  983.05   511.1  983.34   570.3  992.79   585.1  995.27   599.9  998.44
   619.4 1004.43   747.9 1045.95   836.6 1074.32   969.8 1115.23  1008.9 1127.63
#Mann= 3 , 0 , 0
       0     0.1       0   492.7   0.045       0   507.7     0.1       0
Bank Sta=   492.7,   507.7
Exp/Cntr=0.3,0.1

Type RM Length L Ch R = 1 ,1490.8,415.391,400,385.748
XS GIS Cut Line= 3
     1728800.697      308607.862     1728715.908      308107.483
     1728640.641      307659.747
#Sta/Elev= 30
       0 1123.75    61.4 1107.91   133.7 1088.04   155.3 1081.86   181.8 1073.56
   193.9 1069.25   200.7 1066.56   218.0 1059.21   254.1 1041.99   314.3 1014.96
   326.3 1010.13   338.4 1005.82   386.0  990.54   398.6  986.86   406.6  984.94
   437.5  980.05   458.8  977.94   474.2  977.20   489.0  975.99     500  975.41
   507.0  975.09     515  975.52   519.0  975.73   571.5  982.24   579.2  983.48
   592.1  986.07   777.6 1032.24   850.6 1050.84   928.3 1072.04   961.5 1081.86
#Mann= 3 , 0 , 0
       0     0.1       0     500   0.045       0     515     0.1       0
Bank Sta=     500,     515
Exp/Cntr=0.3,0.1

Type RM Length L Ch R = 1 ,1090.8,473.618,465.781,456.66
XS GIS Cut Line= 3
     1729386.246      308227.959     1728962.027      307852.861
     1728612.205      307509.614
#Sta/Elev= 30
       0 1102.96    58.8 1084.16    99.4 1070.03   201.4 1027.17   217.3 1020.98
   233.1 1018.24   252.8 1018.80   264.8 1018.09   276.0 1015.63   312.4 1002.52
   328.2  998.55   334.9  997.93   344.1  994.56   360.3  990.13   368.5  988.56
   396.1  980.18   414.1  977.22   423.3  977.15   467.8  973.04   494.7  972.25
   558.8  972.71   565.9  972.81   573.8  973.84   595.5  978.80   629.1  984.87
   645.9  989.76   848.7 1057.32   930.9 1086.13   965.1 1099.30  1056.4 1130.84
#Mann= 3 , 0 , 0
       0     0.1       0   558.8   0.045       0   573.8     0.1       0
Bank Sta=   558.8,   573.8
Exp/Cntr=0.3,0.1

Type RM Length L Ch R = 1 ,625.1,454.721,464.487,473.908
XS GIS Cut Line= 3
     1729703.260      307816.672     1729245.553      307634.825
     1728770.930      307471.988
#Sta/Elev= 30
       0 1033.73    46.9 1030.12   107.5 1031.23   136.0 1030.91   184.1 1031.24
   209.1 1030.33   235.2 1031.10   248.0 1030.24   272.0 1027.41   311.9 1020.95
   350.2 1015.41   363.0 1012.12   439.6  978.57   452.4  971.81   464.9  965.73
   474.3  964.78   479.9  965.06   490.7  966.63   501.9  967.73   528.4  966.76
   541.0  966.99   566.1  968.29   623.4  973.37   632.7  974.31   641.4  975.84
   651.4  978.85   679.0  988.54   779.4 1022.17   905.0 1063.03   994.3 1093.96
#Mann= 3 , 0 , 0
       0     0.1       0   464.9   0.045       0   479.9     0.1       0
Bank Sta=   464.9,   479.9
Exp/Cntr=0.3,0.1

Type RM Length L Ch R = 1 ,160.6,159.905,160.564,160.127
XS GIS Cut Line= 3
     1729841.702      307610.334     1729488.351      307238.085
     1729131.457      306890.408
#Sta/Elev= 30
       0  988.14    50.4  981.86   122.0  975.37   135.7  973.09   152.4  968.63
   165.0  967.18   173.7  967.41   197.8  970.90   219.6  969.51   263.2  963.60
   303.6  962.23   312.3  961.20   346.1  960.62   397.9  963.14   429.6  963.66
   454.8  962.52   494.8  958.00   496.8  957.87   509.8  958.28   547.1  965.08
   568.1  967.12   614.3  964.96   684.1  963.93   717.3  964.62   780.8  968.15
   833.3  968.22   848.9  969.37   882.9  979.57   934.0  986.99  1011.5 1006.37
#Mann= 3 , 0 , 0
       0     0.1       0   494.8   0.045       0   509.8     0.1       0
Bank Sta=   494.8,   509.8
Exp/Cntr=0.3,0.1